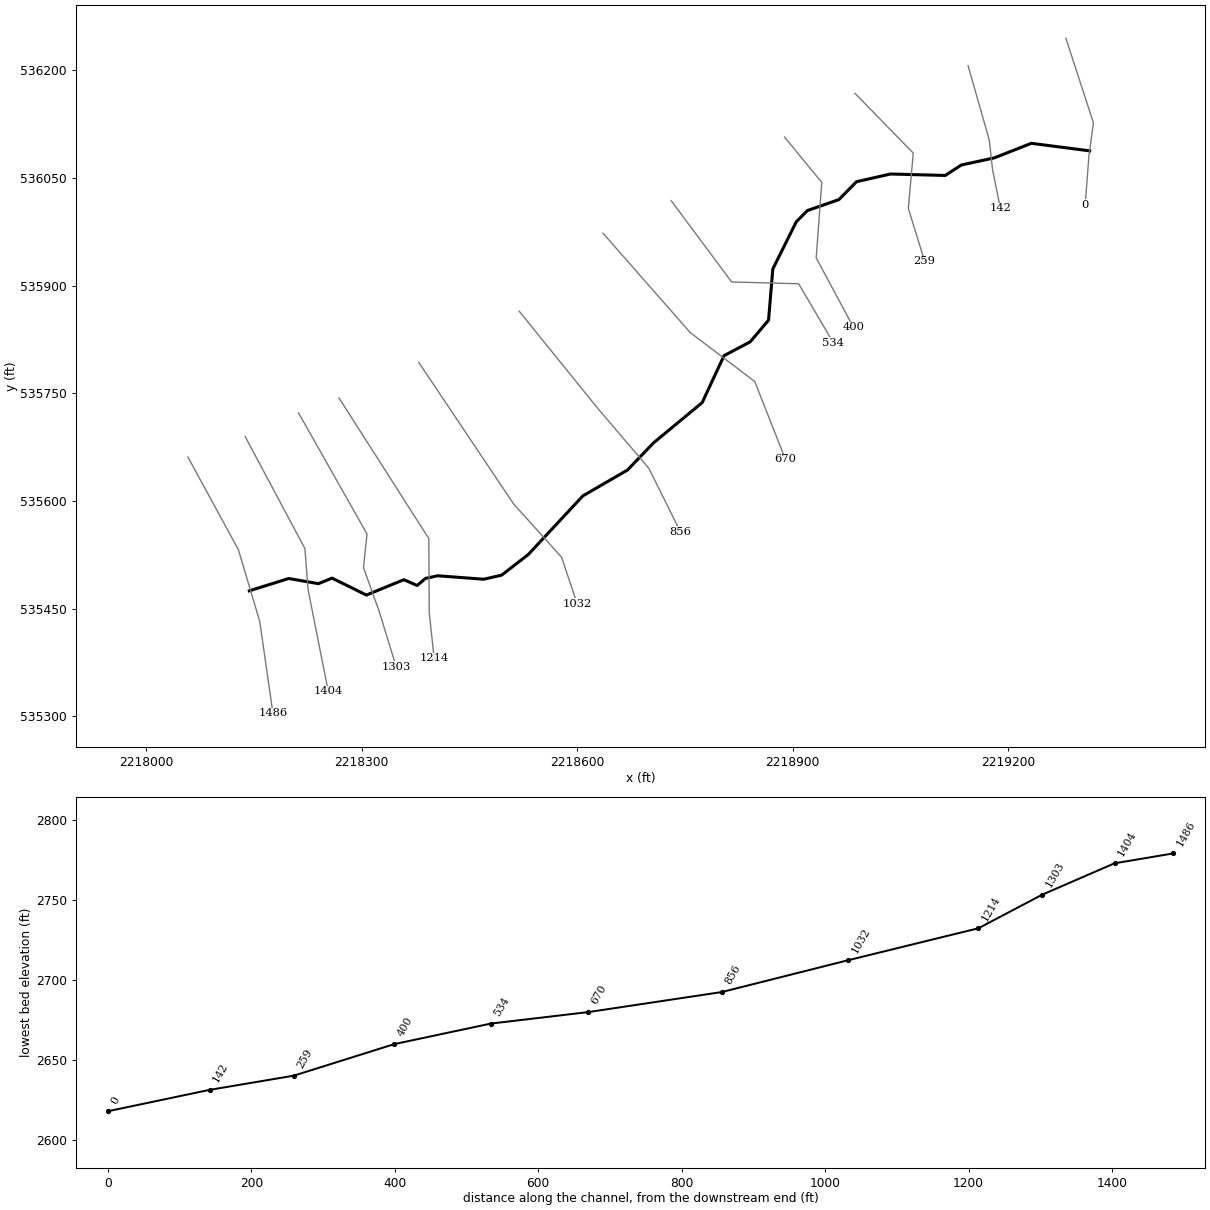
--- BLKHLRN.prj (project) ---

Proj Title=BLKHLRN
Current Plan=p01
Default Exp/Contr=0,0
English Units
Geom File=g01
Flow File=f01
Plan File=p01
BEGIN DESCRIPTION:
----------MODEL BY WOOD PLC 2022----------
AFH study
Randolph County, WV
HEC-RAS Version: RAS 6.2
Vertical Datum: NAVD88
Projection: NAD 1983 StatePlane West Virginia S FIPS 4702 (US Feet)
Terrain: 1-meter LIDAR (FEMA Region III 3DEP collected 2016-2018)
Land Use: 2019 NLCD
Hydrologic Method:
WV SIR2010-5033 regression equations
Additional Model Notes:
Blackhole Run extends outside of the county boundary.
END DESCRIPTION:
DSS Export Rating Curves= 0
DSS Export Rating Curve Sorted= 0
DSS Export Volume Flow Curves= 0
DXF OffsetX= 0
DXF OffsetY= 0
DXF ScaleX= 0
DXF ScaleY= 0

--- BLKHLRN.p01 (plan) ---

Plan Title=Floodplain
Program Version=6.20
Short Identifier=Floodplain
Geom File=g01
Flow File=f01
Subcritical Flow
K Sum by GR= 0
Std Step Tol= 0.01
Critical Tol= 0.01
Num of Std Step Trials= 20
Max Error Tol= 0.3
Flow Tol Ratio= 0.001
Split Flow NTrial= 30
Split Flow Tol= 0.02
Split Flow Ratio= 0.02
Log Output Level= 0
Friction Slope Method= 1
Unsteady Friction Slope Method= 2
Unsteady Bridges Friction Slope Method= 1
Parabolic Critical Depth
Global Vel Dist= 0 , 0 , 0
Global Log Level= 0
CheckData=True
Encroach Param=-1 ,0,0, 0
Mapping Interval=1HOUR
Computation Time Step Use Courant=        0
Computation Time Step Use Time Series=    0
Computation Time Step Count To Double=0
Computation Time Step Max Doubling=0
Computation Time Step Max Halving=0
Computation Time Step Residence Courant=0
Run HTab= 0
Run UNet= 0
Run Sediment= 0
Run PostProcess= 0
Run WQNet= 0
Run RASMapper=-1
UNET Theta= 0
UNET Theta Warmup= 0
UNET ZTol= 0
UNET ZSATol= 0
UNET MxIter= 0
UNET Max Iter WO Improvement= 0
UNET MaxInSteps= 0
UNET DtIC= 0
UNET DtMin= 0
UNET MaxCRTS= 0
UNET WFStab= 0
UNET SFStab= 0
UNET WFX= 1
UNET SFX= 1
UNET Gravity=32.174
UNET 1D Methodology=Finite Difference
UNET DSS MLevel= 1
UNET Pardiso=0
UNET DZMax Abort= 0
UNET Use Existing IB Tables= 0
UNET Froude Reduction=False
UNET Froude Limit= 0
UNET Froude Power= 0
UNET D1 Cores= 0
UNET WindReference=Eulerian
UNET WindDragFormulation=Hsu (1988)
UNET D2 Coriolis=0
UNET D2 Cores= 0
UNET D2 Theta= 1
UNET D2 Theta Warmup= 1
UNET D2 Z Tol= 0.01
UNET D2 Volume Tol= 0.01
UNET D2 Max Iterations= 20
UNET D2 Equation= 0
UNET D2 RampUpFraction=0.1
UNET D2 TimeSlices= 1
UNET D2 Turbulence Formulation=Non-Conservative (original)
UNET D2 Eddy Viscosity=0.3
UNET D2 Transverse Eddy Viscosity=0.1
UNET D2 Smagorinsky Mixing=0
UNET D2 BCVolumeCheck=0
UNET D2 Cores=0
UNET D2 SolverType=PARDISO (Direct)
UNET D2 Minimum Iterations= 2147483647
UNET D2 Maximum Iterations= 2147483647
UNET D2 Restart Number= 10
UNET D2 Relaxation Coeff=1.3
UNET D2 SOR Precondition Iterations= 10
UNET D2 ILUT Maximum Fill= 8
UNET D2 ILUT Tolerance=1E-08
UNET D1D2 MaxIter= 0
UNET D1D2 ZTol=0.01
UNET D1D2 QTol=0.1
UNET D1D2 MinQTol=1
Write IC File= 0
Write IC File at Fixed DateTime=0
Write IC File at Sim End=0
Echo Input=False
Echo Parameters=False
Echo Output=False
Write Detailed= 0
HDF Write Warmup=0
HDF Write Time Slices=0
HDF Flush=0
HDF Compression= 1
HDF Chunk Size= 1
HDF Spatial Parts= 1
HDF Use Max Rows=0
HDF Fixed Rows= 1
Calibration Method= 0
Calibration Iterations= 20
Calibration Max Change=0.05
Calibration Tolerance=0.2
Calibration Maximum=1.5
Calibration Minimum=0.5
Calibration Optimization Method= 1
WQ AD Non Conservative
WQ ULTIMATE=-1
WQ Max Comp Step=1HOUR
WQ Output Interval=15MIN
WQ Output Selected Increments= 0
WQ Output face flow=0
WQ Output face velocity=0
WQ Output face area=0
WQ Output face dispersion=0
WQ Output cell volume=0
WQ Output cell surface area=0
WQ Output cell continuity=0
WQ Output cumulative cell continuity=0
WQ Output face conc=0
WQ Output face dconc_dx=0
WQ Output face courant=0
WQ Output face peclet=0
WQ Output face adv mass=0
WQ Output face disp mass=0
WQ Output cell mass=0
WQ Output cell source sink temp=0
WQ Output nsm pathways=0
WQ Output nsm derived pathways=0
WQ Create Restart=0
WQ Fixed Restart=0
WQ System Summary=0
WQ Write To DSS=0
Sorting and Armoring Iterations= 10
XS Update Threshold= 0.02
Bed Roughness Predictor= 0
Hydraulics Update Threshold= 0.02
Energy Slope Method= 1
Volume Change Method= 1
Sediment Retention Method= 0
Sediment TS Multiplier= 1
Warm Up Method= 0
XS Weighting Method= 0
Number of US Weighted Cross Sections= 1
Number of DS Weighted Cross Sections= 1
Upstream XS Weight=0
Main XS Weight=1
Downstream XS Weight=0
Number of DS XS's Weighted with US Boundary= 1
Upstream Boundary Weight= 1
Weight of XSs Associated with US Boundary= 0
Number of US XS's Weighted with DS Boundary= 1
Downstream Boundary Weight= 0.5
Weight of XSs Associated with DS Boundary= 0.5
Percentile Method= 0
Sediment Output Level= 3
Mass or Volume Output= 0
Output Increment Type= 1
Profile and TS Output Increment= 1
Transport Output Increment 1
XS Output Flag= 0
XS Output Increment= 10
Read HDF5 Sediment Hotstart= 0
Sediment Hotstart Type= 0
Write Gradation File= 0
Read Gradation Hotstart= 0
Write HDF5 File= 1
Write Binary Output= 1
Write DSS Sediment File= 0
DSS Sediment Output Type= 1
SV Curve= 0
Specific Gage Flag= 0
Subcell Erosion Methods= 0
Subcell Deposition Methods= 0
Advection Scheme= 1
Matrix Solver= 0
Implicit Weighting Factor= 1
Maximum Outer Loop Convergence Iterations= 5
Convergence Maximum Absolute= 0.001
Convergence RMSE= 0.0001
Grain Fractions Max Abs Error= 0.001
Max Subgrid Regions= 1
Max Subgrid Length Scale= 3.402823E+38
Initial Layer Thickness= 3.402823E+38
Min Layer Thickness= 3.402823E+38
Max Layer Thickness= 3.402823E+38
Number of Layers= 5

--- BLKHLRN.f01 (steady flow) ---

Flow Title=Flow
Program Version=6.20
Number of Profiles= 1
Profile Names=P100yr
River Rch & RM=BLKHLRN,Main,1486
     365
Boundary for River Rch & Prof#=BLKHLRN,Main            , 1
Up Type= 0
Dn Type= 3
Dn Slope=0.10245
DSS Import GetInterval= 0
DSS Import GetPeak= 0
DSS Import FillOption= 0

--- BLKHLRN.g01 (geometry) ---

Geom Title=Geometry
Program Version=6.20

River Reach=BLKHLRN         ,Main
Reach XY= 30
      2218143.85      535475.044     2218198.538      535492.232
2218239.96911256535485.026682417     2218258.954      535492.752
     2218306.717      535469.1872218358.86286649535490.582349431
2218377.26828031535482.5049986912218388.93445013535492.330316507
2218406.03106683535496.043244332     2218469.892       535491.19
     2218494.892      535496.919     2218531.871      535525.565
     2218607.913      535607.336     2218669.892      535643.273
      2218706.35      535681.294     2218773.917      535737.298
     2218804.267      535802.648     2218840.725      535821.919
     2218866.246      535852.127      2218872.18      535923.359
     2218904.787      535989.1072218920.26139665536004.785907655
2218964.18746699536020.0935110032218988.59400527536044.997304307
2219036.02591093536055.733231403     2219112.079       536053.69
     2219134.475      536068.273     2219180.309      536078.169
     2219231.871      536098.4812219313.07064028 536087.95741234

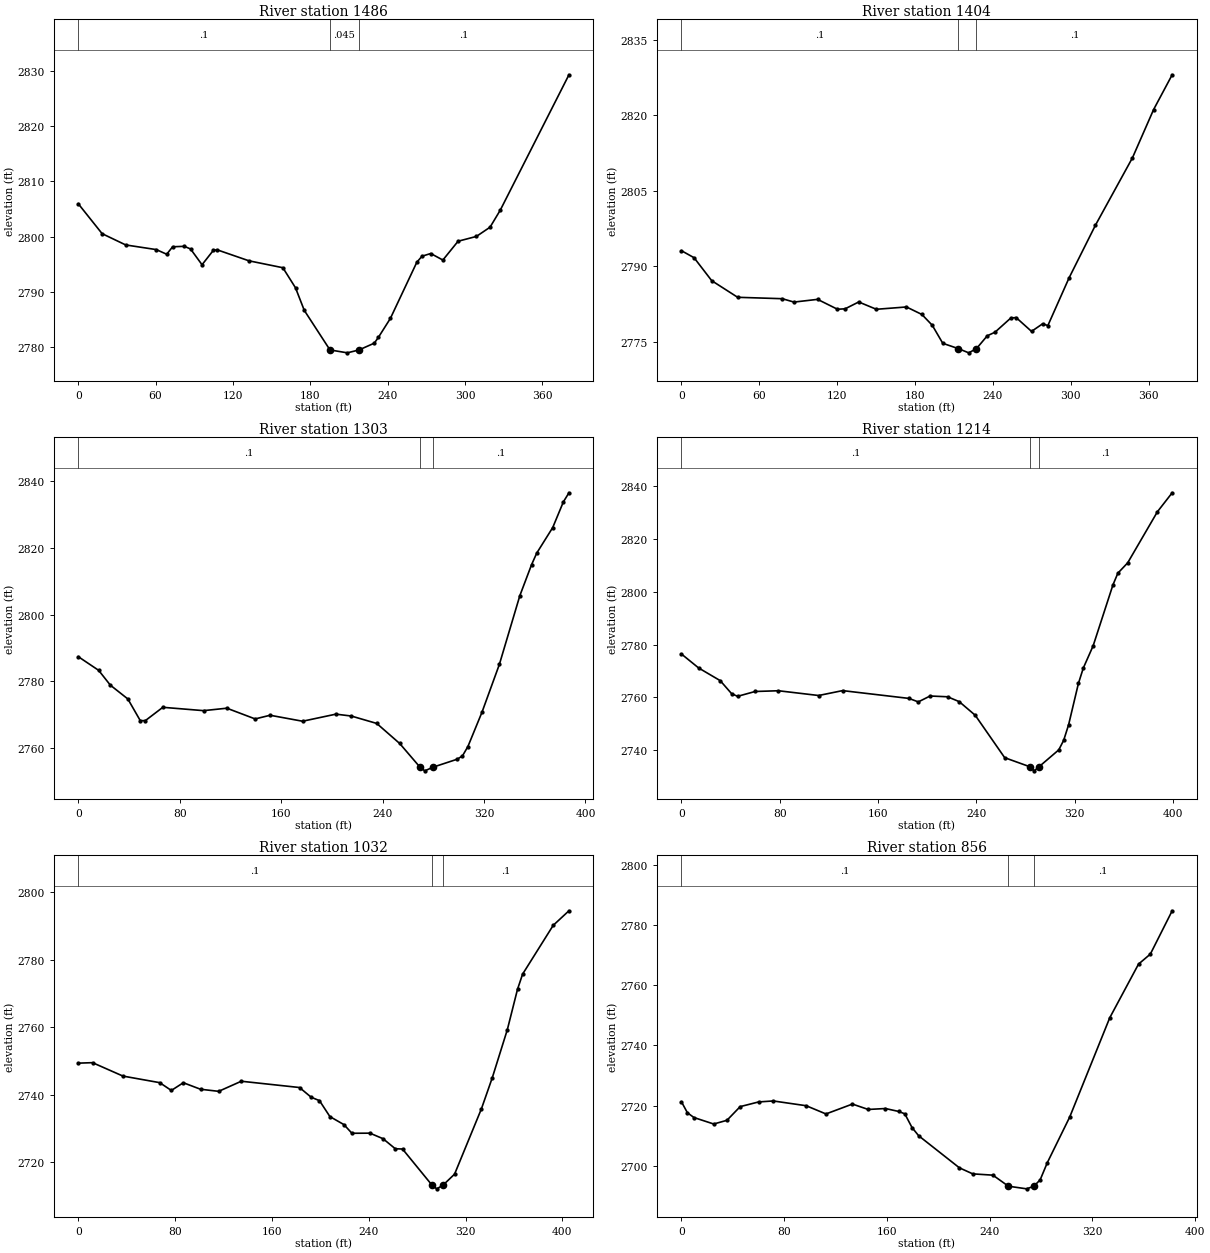
Type RM Length L Ch R = 1 ,1486    ,83.9,82.1,80.5
XS GIS Cut Line= 4
2218058.36082976535661.465622355  2218128.679096535532.223394693
2218158.32032837535432.4553442592218176.68533592535304.343451287
#Sta/Elev= 30
       0 2805.93    18.5 2800.52    36.8 2798.48    60.5 2797.64    68.6  2796.8
    73.2 2798.15    82.3 2798.23    87.1 2797.75      96  2794.9   104.8 2797.51
   107.7  2797.6   132.4 2795.61   158.7 2794.36   168.5 2790.73   175.3 2786.65
  195.232779.496   208.7 2778.97  217.772779.495   229.6 2780.72   232.8 2781.77
   242.1  2785.2   262.6 2795.35   266.6 2796.44   273.4 2796.93   282.8 2795.75
   294.6 2799.15   308.8 2800.02   319.4 2801.69   327.3 2804.76   380.6 2829.25
#Mann= 3, -1 ,  0
       0     0.1       0  195.23   0.045       0  217.77     0.1       0
Bank Sta=195.23,217.77
XS Rating Curve= 0 ,0
Exp/Cntr(USF)=0,0
Exp/Cntr=0.3,0.1

Type RM Length L Ch R = 1 ,1404    ,97.8,100.8,100.2
XS GIS Cut Line= 4
2218138.15935489535689.7320666312218221.13899572535533.964446569
2218225.58101036535476.7450418112218253.64700063535335.132520137
#Sta/Elev= 30
       0 2793.08     9.7 2791.69    23.3 2787.13    43.3 2783.83    77.7 2783.55
    86.7 2782.88   104.9 2783.42   120.2 2781.46   126.1 2781.54   136.6  2782.9
   150.2 2781.45   173.4 2781.91   185.3 2780.42   193.3 2778.27   201.4 2774.69
   213.52773.628   221.4  2772.8  227.36 2773.64   235.7 2776.19   241.6 2776.89
   253.8 2779.71   257.9 2779.81   269.8 2777.06   278.3 2778.56   282.4 2778.22
   298.7 2787.67   319.1 2798.17   347.6 2811.54   363.9 2821.12   378.2 2828.02
#Mann= 3, -1 ,  0
       0     0.1       0   213.5   0.045       0  227.36     0.1       0
Bank Sta=213.5,227.36
XS Rating Curve= 0 ,0
Exp/Cntr(USF)=0,0
Exp/Cntr=0.3,0.1

Type RM Length L Ch R = 1 ,1303    ,89.3,89,86.5
XS GIS Cut Line= 5
2218212.11363947535723.2332985672218307.55809997535554.267743945
2218302.65271225535507.517867848 2218324.9981167535444.933602923
2218348.25770812535368.910020758
#Sta/Elev= 30
       0 2787.38    16.1 2783.28    25.3 2778.85    39.1 2774.72    48.9 2768.23
    52.9 2768.23    66.7 2772.22    98.8 2771.22   117.2 2771.95   139.5 2768.74
   151.3 2769.84   176.9 2768.05   203.2 2770.17   215.3 2769.61   235.4 2767.39
   253.5 2761.39  269.432754.335   273.3  2753.2  280.072754.333   298.8 2756.67
     303 2757.67   307.3 2760.47   318.4 2770.74   332.1 2785.04   348.3 2805.68
   357.5  2814.9   361.6 2818.39   374.2 2826.03   382.6 2833.72     387 2836.44
#Mann= 3, -1 ,  0
       0     0.1       0  269.43   0.045       0  280.07     0.1       0
Bank Sta=269.43,280.07
XS Rating Curve= 0 ,0
Exp/Cntr(USF)=0,0
Exp/Cntr=0.3,0.1

Type RM Length L Ch R = 1 ,1214    ,178.1,182.1,184.2
XS GIS Cut Line= 4
2218268.63468247535743.6919451342218393.60369522535547.832547742
2218394.13616548535444.6950389922218400.93928296535381.256892179
#Sta/Elev= 30
       0 2776.41      14 2771.13    31.5 2766.35    40.9 2761.36    45.7 2760.41
    59.9 2762.24    78.9 2762.52   111.6 2760.72   131.1 2762.57   185.1 2759.62
   192.7  2758.3   202.3 2760.53   216.5 2760.24     226  2758.4     239 2753.26
     263 2737.19  283.46 2733.76     287 2732.21  290.95 2733.76     307 2740.14
     311 2743.75     315 2749.61     323 2765.28     327 2771.13     335 2779.54
   351.1 2802.58   355.1 2807.01   363.1 2810.93   387.3 2830.27   399.3 2837.44
#Mann= 3, -1 ,  0
       0     0.1       0  283.46   0.045       0  290.95     0.1       0
Bank Sta=283.46,290.95
XS Rating Curve= 0 ,0
Exp/Cntr(USF)=0,0
Exp/Cntr=0.3,0.1

Type RM Length L Ch R = 1 ,1032    ,175.6,175.8,176.1
XS GIS Cut Line= 4
2218379.67004153535793.1111625542218511.35743965535596.338313587
2218578.34137505535521.7613400412218599.99284419 535456.86999888
#Sta/Elev= 30
       0 2749.41    11.8 2749.55    36.9 2745.58    67.3 2743.63    76.9 2741.32
    86.8 2743.61     101 2741.68     116 2741.06   134.7 2744.05   182.8 2742.19
   192.4 2739.32   199.3  2738.3   207.9 2733.58   219.5  2731.2   226.1 2728.64
     241 2728.67   251.8 2727.03   261.9 2724.06   267.9 2723.97  292.312713.252
   296.2 2712.18  301.292713.255   310.9 2716.53   333.1  2735.9   342.1 2745.13
   354.5 2759.34   362.9 2771.29   367.1 2775.77   392.4 2790.23   405.4 2794.54
#Mann= 3, -1 ,  0
       0     0.1       0  292.31   0.045       0  301.29     0.1       0
Bank Sta=292.31,301.29
XS Rating Curve= 0 ,0
Exp/Cntr(USF)=0,0
Exp/Cntr=0.3,0.1

Type RM Length L Ch R = 1 ,856     ,183.6,186.1,187.6
XS GIS Cut Line= 4
2218519.22731072535864.7207700382218627.64785413535730.410388302
 2218699.5813505535645.9232640862218743.44465946535557.701827726
#Sta/Elev= 30
       0 2721.22     4.6  2717.6     9.7 2716.01    25.1 2713.86    35.4 2715.09
    45.7 2719.63    60.1 2721.19    71.5 2721.51    97.1 2719.93   112.5  2717.2
   133.1 2720.48   145.4 2718.69   158.8    2719   169.1 2718.03   173.9 2717.24
   179.5  2712.7   184.7 2709.96   216.4 2699.32   226.8 2697.31   242.5 2696.88
  254.572693.215   268.8 2692.34  274.422693.215   279.3 2695.33   284.9 2701.05
   302.3 2716.16   333.5 2749.13   355.9 2766.94   365.1 2770.26   382.1 2784.64
#Mann= 3, -1 ,  0
       0     0.1       0  254.57   0.045       0  274.42     0.1       0
Bank Sta=254.57,274.42
XS Rating Curve= 0 ,0
Exp/Cntr(USF)=0,0
Exp/Cntr=0.3,0.1

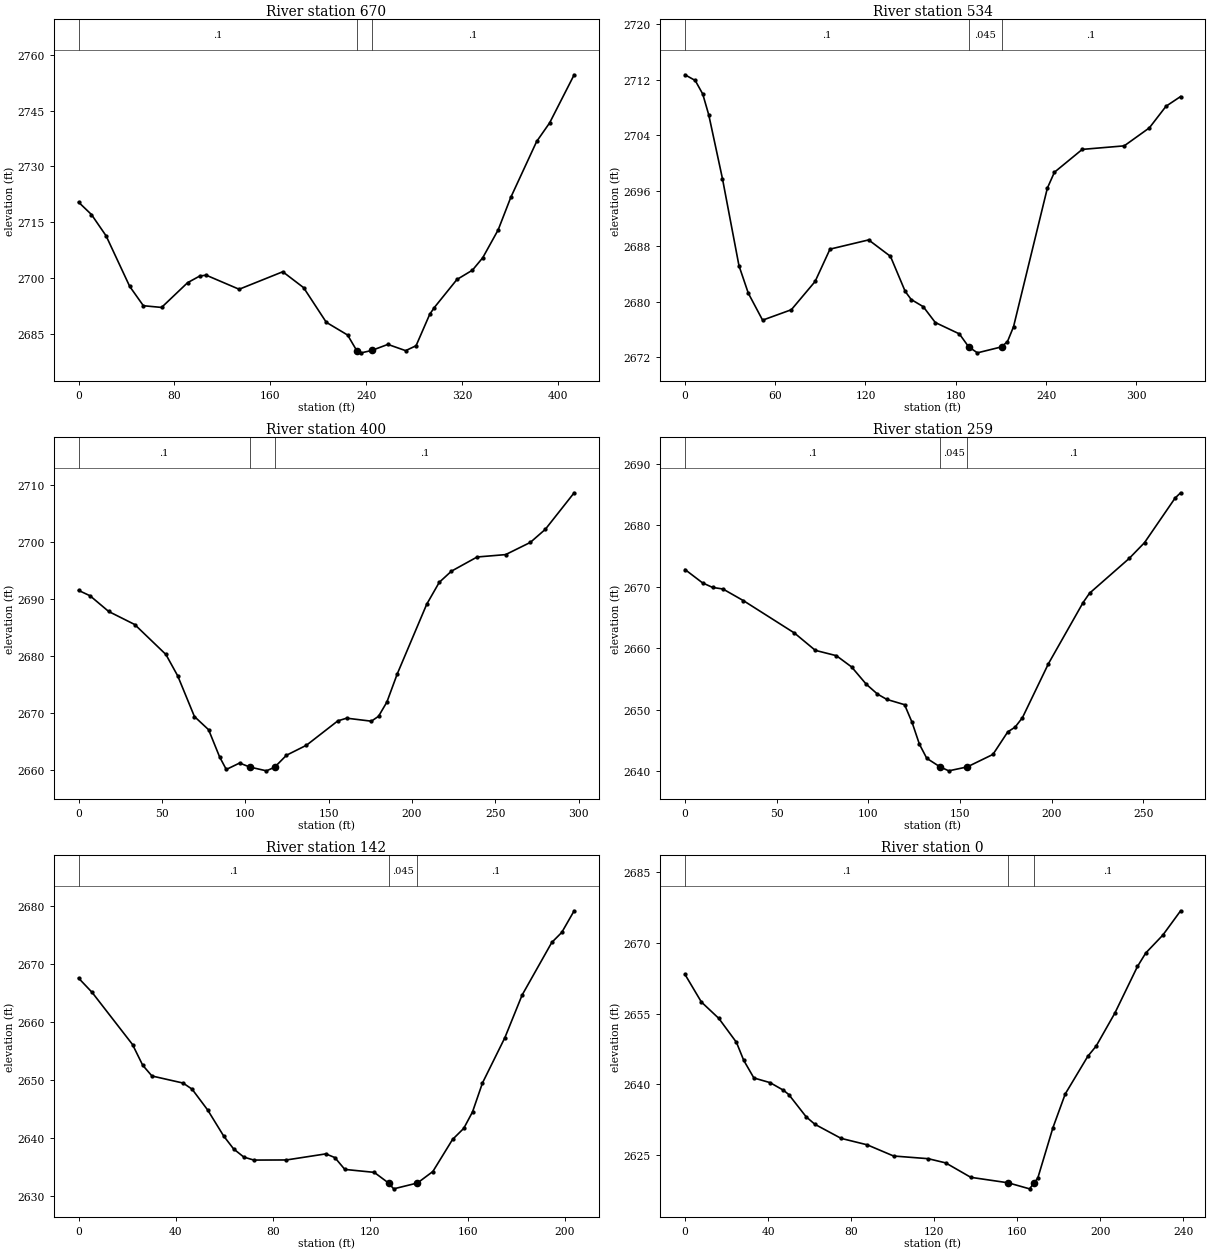
Type RM Length L Ch R = 1 ,670     ,130.5,135.9,144
XS GIS Cut Line= 4
2218635.89145241535973.302916361 2218757.1973329535834.847828882
2218847.02388874535766.7017421042218889.78921612535658.118765547
#Sta/Elev= 30
       0 2720.39    10.8 2717.05      23 2711.32    42.7 2697.71    54.1 2692.51
    69.3 2692.05      91 2698.71   101.2 2700.51   106.5 2700.73     134 2696.94
   170.4 2701.65   187.8 2697.37   206.7 2688.05   224.5 2684.62  232.082680.448
   235.9 2679.83   244.5 2680.46   258.1  2682.1   272.9 2680.42   281.6 2681.74
     293  2690.2   296.8 2692.01   315.7 2699.57   328.6 2702.07   337.2 2705.41
   350.1 2712.92   360.6 2721.65   382.2 2736.71     393  2741.7   413.5 2754.66
#Mann= 3, -1 ,  0
       0     0.1       0  232.08   0.045       0   244.5     0.1       0
Bank Sta=232.08,244.5
XS Rating Curve= 0 ,0
Exp/Cntr(USF)=0,0
Exp/Cntr=0.3,0.1

Type RM Length L Ch R = 1 ,534     ,149.8,134.5,123.2
XS GIS Cut Line= 4
2218730.76422876536018.6390849932218814.86102176535905.346635091
2218908.18117366535902.7859258422218956.24535083535820.805990786
#Sta/Elev= 30
       0  2712.7     6.8 2711.88    11.8 2709.93    15.8 2706.93    24.9 2697.75
    35.9 2685.19    42.1 2681.23    51.6 2677.35    70.7 2678.85    86.5 2682.92
    96.4 2687.58   122.1 2688.91   136.6 2686.54   146.4 2681.49   150.4 2680.32
   158.4 2679.29   166.4 2677.01   182.4 2675.37  188.61  2673.5   194.4 2672.64
  210.442673.498   214.4 2674.27   218.4 2676.39   240.9 2696.37   245.6 2698.66
   264.1 2701.95     292 2702.46   308.7 2705.05   319.8 2708.17   329.5 2709.57
#Mann= 3, -1 ,  0
       0     0.1       0  188.61   0.045       0  210.44     0.1       0
Bank Sta=188.61,210.44
XS Rating Curve= 0 ,0
Exp/Cntr(USF)=0,0
Exp/Cntr=0.3,0.1

Type RM Length L Ch R = 1 ,400     ,137.9,140.3,137.9
XS GIS Cut Line= 4
2218888.45385421536107.2047402072218940.29292624536044.023590845
2218932.53008918535938.8477533792218984.54812702 535841.93645903
#Sta/Elev= 30
       0 2691.52     6.9 2690.57    18.1 2687.81    33.7 2685.52    52.4 2680.26
    59.5 2676.49    69.5 2669.36      78 2667.04    84.6 2662.27    88.6 2660.06
    96.6 2661.19   102.72660.485   112.7 2659.82   117.62660.457   124.7 2662.56
   136.7 2664.32   155.5  2668.6   160.8 2669.07   175.6 2668.54   179.9  2669.4
   184.9  2671.9   191.1 2676.83   208.8 2689.09   216.3 2692.93   223.6 2694.89
     239 2697.38   256.1  2697.8   270.9 2699.94   279.9 2702.24   297.2 2708.66
#Mann= 3, -1 ,  0
       0     0.1       0   102.7   0.045       0   117.6     0.1       0
Bank Sta=102.7,117.6
XS Rating Curve= 0 ,0
Exp/Cntr(USF)=0,0
Exp/Cntr=0.3,0.1

Type RM Length L Ch R = 1 ,259     ,115.2,117.4,118.5
XS GIS Cut Line= 4
2218986.52767568536168.0204644692219067.61655484536084.838533444
2219060.71911771536007.963647087 2219083.4023559535934.375696201
#Sta/Elev= 30
       0 2672.84     9.6 2670.66    15.1 2669.92    20.7 2669.67    31.9 2667.77
    59.7 2662.51    71.1 2659.69    82.6 2658.82    90.9 2656.99    98.9 2654.18
     105 2652.58   110.1 2651.71   119.8 2650.85   123.9 2647.96   127.9 2644.42
   131.9 2642.13   139.12640.743   143.9 2640.09  153.99 2640.73     168 2642.76
   176.1 2646.43   180.1  2647.2   184.1 2648.74   198.3 2657.53   217.2 2667.47
   220.7 2668.98   242.3 2674.63   250.7 2677.21   267.4 2684.47   270.4 2685.32
#Mann= 3, -1 ,  0
       0     0.1       0   139.1   0.045       0  153.99     0.1       0
Bank Sta=139.1,153.99
XS Rating Curve= 0 ,0
Exp/Cntr(USF)=0,0
Exp/Cntr=0.3,0.1

Type RM Length L Ch R = 1 ,142     ,143.2,141.7,140.2
XS GIS Cut Line= 4
2219143.90262806536206.560109266 2219173.4177381536102.769922858
2219177.91238349536061.8426093162219188.74479761536008.201168446
#Sta/Elev= 30
       0 2667.57     5.6 2665.09    22.2 2656.11    26.4 2652.53    30.2 2650.68
      43 2649.46    46.7 2648.41    53.1 2644.82    59.7 2640.32    63.8 2638.09
      68 2636.69    72.1 2636.18    85.5  2636.2   101.7 2637.25   105.4 2636.61
   109.5 2634.57   121.6 2634.06  127.462632.231   129.6 2631.22  139.382632.229
   145.7 2634.21   153.8 2639.74   158.4 2641.65     162 2644.48   166.1 2649.48
   175.3 2657.28   182.4 2664.64   194.6 2673.71   198.7 2675.44   203.8 2679.17
#Mann= 3, -1 ,  0
       0     0.1       0  127.46   0.045       0  139.38     0.1       0
Bank Sta=127.46,139.38
XS Rating Curve= 0 ,0
Exp/Cntr(USF)=0,0
Exp/Cntr=0.3,0.1

Type RM Length L Ch R = 1 ,0       ,,,
XS GIS Cut Line= 4
2219279.99970317536244.719429136  2219318.274455536126.915718593
2219312.05450354536081.7405514532219306.73852512536012.585331427
#Sta/Elev= 30
       0 2663.33     7.9 2657.48    16.3 2654.01    24.8 2648.93    28.3 2645.12
    33.2 2641.38      41 2640.39    47.4 2638.79      50 2637.87    58.4 2633.14
    62.6 2631.56    75.2 2628.58    87.8 2627.21   100.5 2624.84   117.2 2624.27
   125.6 2623.38   137.7 2620.32   155.7 2619.16     166 2617.88   168.32619.172
     170 2620.19   177.3 2630.87   183.2 2637.99   194.1 2645.99   198.1 2648.14
   207.1 2655.12     218 2665.01     222 2667.87   230.2 2671.65   238.8 2676.82
#Mann= 3, -1 ,  0
       0     0.1       0   155.7   0.045       0   168.3     0.1       0
Bank Sta=155.7,168.3
XS Rating Curve= 0 ,0
Exp/Cntr(USF)=0,0
Exp/Cntr=0.3,0.1
LCMann Table=0

Chan Stop Cuts=-1
Use User Specified Reach Order=0
Composite Channel Slope=5